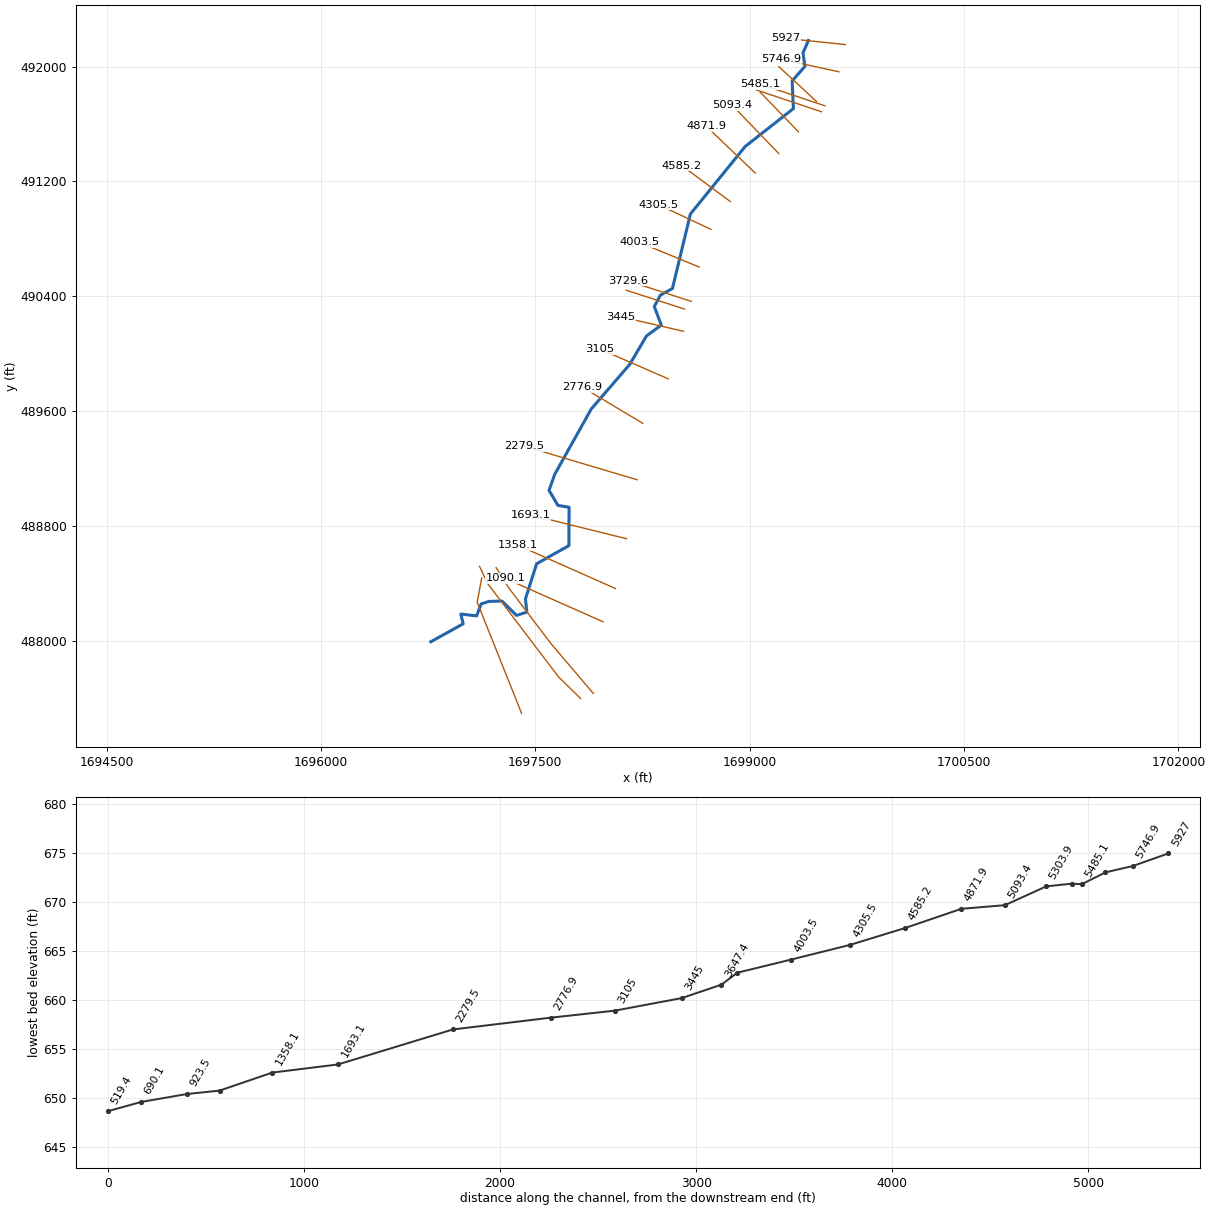
--- BiggerBr.prj (project) ---

Proj Title=BiggerBr
Current Plan=p01
Default Exp/Contr=0,0
English Units
Geom File=g01
Flow File=f01
Plan File=p01
BEGIN DESCRIPTION:
AMEC Environment & Infrastructure, 2013
Projection: NAD 1983 State Plane West Virginia South FIPS 4702 (US Feet)
Vertical Datum: NAVD 1988
END DESCRIPTION:
DSS Export Rating Curves= 0
DSS Export Rating Curve Sorted= 0
DSS Export Volume Flow Curves= 0
DXF OffsetX= 0
DXF OffsetY= 0
DXF ScaleX= 0
DXF ScaleY= 0

--- BiggerBr.p01 (plan) ---

Plan Title=Floodplain
Program Version=4.00
Geom File=g01
Flow File=f01
K Sum by GR=0
Std Step Tol=0.01
Critical Tol=0.01
Num of Std Step Trials=20
Max Error Tol=0.3
Flow Tol Ratio=0.001
Split Flow NTrial=30
Split Flow Tol=0.02
Split Flow Ratio=0.02
Log Output Level=0
Friction Slope Method=1
Unsteady Friction Slope Method=2
Unsteady Bridges Friction Slope Method=1
Global Log Level=0
CheckData=False
Run HTab=0
Run UNet=0
Run PostProcess=0
UNET Theta=0
UNET Theta Warmup=0
UNET ZTol=0
UNET ZSATol=0
UNET MxIter=0
UNET MaxInSteps=0
UNET DtIC=0
UNET DtMin=0
UNET MaxCRTS=0
UNET WFStab=0
UNET SFStab=0
UNET WFX=0
UNET SFX=0
UNET DSS MLevel=0
UNET DZMax Abort=0
UNET Convert EG Bridges=0
UNET Use Existing IB Tables=0
UNET Froude Limit=0
UNET Froude Power=0
Write IC File=0
Echo Input=False
Echo Output=False
Write Detailed=0

--- BiggerBr.f01 (steady flow) ---

Flow Title=USGS Regress. Eqn. (2010) - Western-Plateaus
Program Version=4.10
Number of Profiles= 1
Profile Names=P100yr
River Rch & RM=BiggerBr,Main            ,5927
     885
River Rch & RM=BiggerBr,Main            ,4871.9
     986
River Rch & RM=BiggerBr,Main            ,4585.2
    1066
River Rch & RM=BiggerBr,Main            ,2776.9
    1133
River Rch & RM=BiggerBr,Main            ,1693.1
    1165
River Rch & RM=BiggerBr,Main            ,519.4
    1214
Boundary for River Rch & Prof#=BiggerBr,Main            , 1
Up Type= 0
Dn Type= 3
Dn Slope=0.00556
DSS Import GetInterval= 0
DSS Import GetPeak= 0
DSS Import FillOption= 0

--- BiggerBr.g01 (geometry) ---

Geom Title=USGS 3m DEM
Program Version=4.10

River Reach=BiggerBr        ,Main
Reach XY= 30
     1699411.269      492182.051     1699372.901      492095.188
     1699387.484      492002.132     1699297.206      491900.743
     1699306.234      491707.688     1698968.476       491443.51
     1698585.514      490973.457     1698459.732      490454.892
      1698375.01       490407.67     1698332.728      490328.672
      1698382.15       490199.98     1698278.851      490124.893
     1698160.101      489925.067     1697891.921       489615.75
     1697636.887      489161.757     1697596.262      489049.257
     1697658.241      488944.048     1697736.366      488931.028
     1697735.324       488663.84     1697509.282      488537.278
     1697431.331      488292.356      1697440.88      488200.342
     1697368.831      488177.772     1697267.269      488277.599
     1697175.255      488274.995     1697121.435      488257.634
     1697089.317        488174.3     1696979.074      488186.945
     1696995.741      488119.237     1696769.092       487994.15

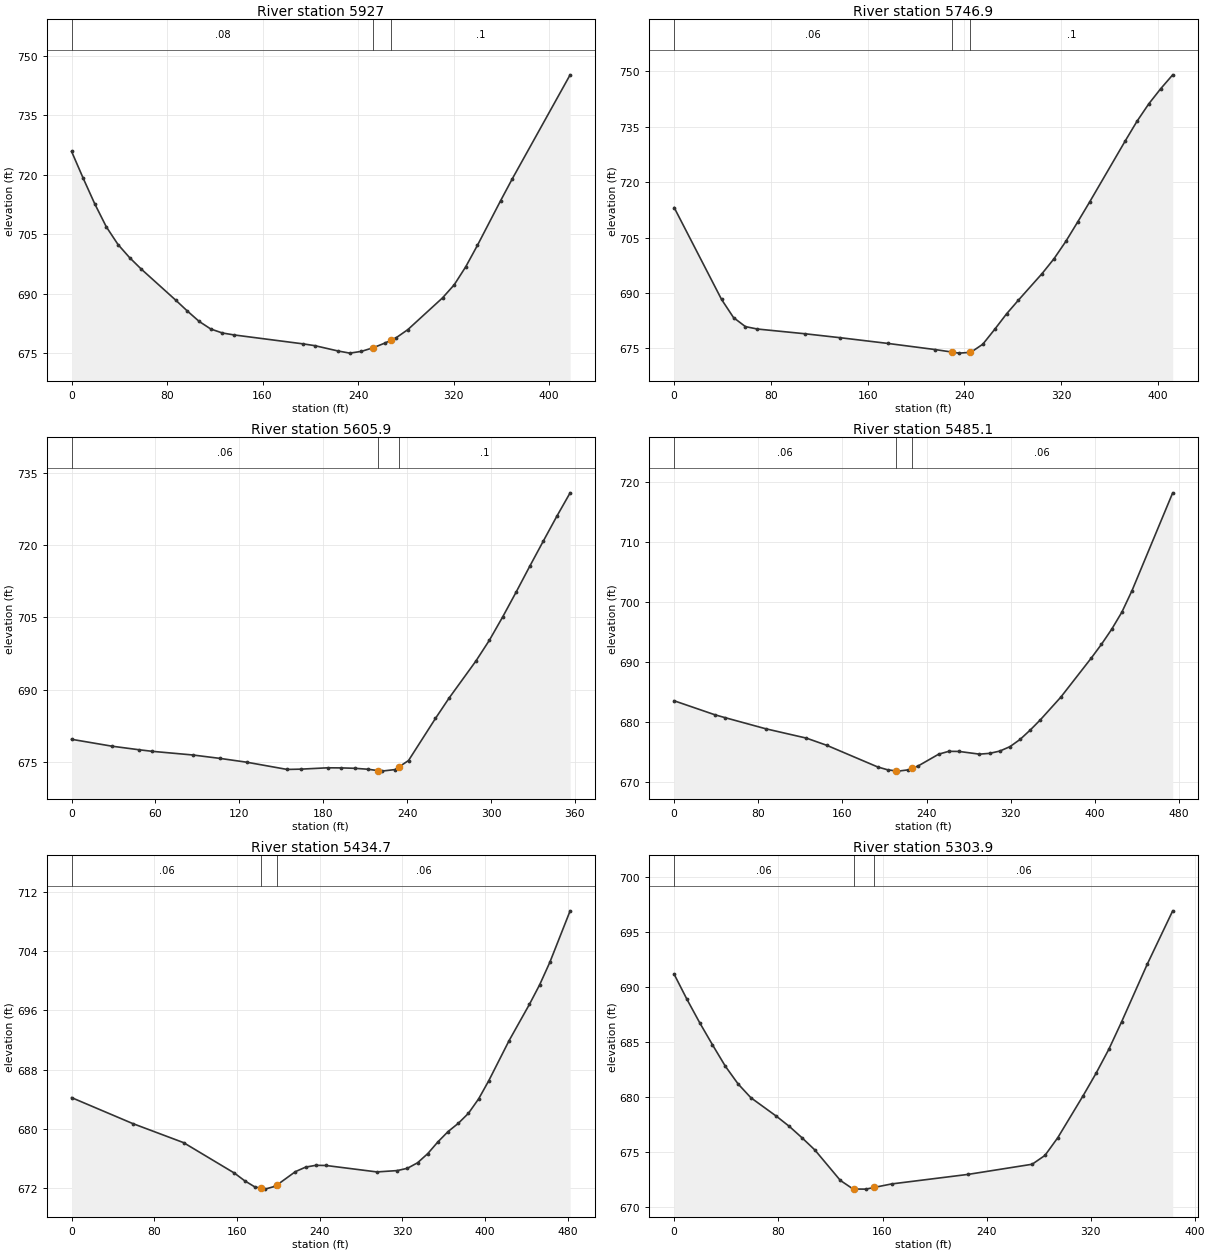
Type RM Length L Ch R = 1 ,5927    ,182.6,180.2,177.5
XS GIS Cut Line= 2
      1699669.64      492153.493     1699254.209      492197.065
#Sta/Elev= 30
       0  725.81     9.7  719.08    19.4  712.62    29.1  706.82    38.9  702.36
    48.6  699.06    58.3  696.19    87.4   688.3    97.1  685.57   106.9  682.98
   116.6  681.07   126.3  680.07     136  679.58   194.3  677.31     204  676.86
   223.4  675.52   233.1  674.99   242.8  675.43   252.9  676.37   262.3   677.5
   267.9   678.3     272  678.88   281.7  680.91   310.8  688.92   320.6  692.22
   330.3  696.79     340  702.14   359.4  713.38   369.1  718.85   417.7  745.13
#Mann= 3 , 0 , 0
       0     .08       0   252.9    .045       0   267.9      .1       0
Bank Sta=252.9,267.9
XS Rating Curve= 0 ,0
Exp/Cntr=0.3,0.1

Type RM Length L Ch R = 1 ,5746.9  ,153.8,141,128.2
XS GIS Cut Line= 2
     1699623.845      491964.055     1699221.076      492051.523
#Sta/Elev= 27
       0  713.13    39.2  688.24    49.1  683.33    58.9  680.89    68.7  680.24
     108  678.96   137.4  677.88   176.6  676.34   215.9  674.67   229.6     674
   235.5  673.71   244.6  673.91   245.3  673.93   255.2  676.13     265  680.14
   274.8  684.33   284.6  688.04   304.2  695.25     314  699.24   323.8  703.95
   333.6   709.2   343.5  714.62   372.9  731.14   382.7   736.5   392.5  741.24
   402.3  745.31   412.2  749.06
#Mann= 3 , 0 , 0
       0     .06       0   229.6    .045       0   244.6      .1       0
Bank Sta=229.6,244.6
XS Rating Curve= 0 ,0
Exp/Cntr=0.3,0.1

Type RM Length L Ch R = 1 ,5605.9  ,109.8,120.8,129
XS GIS Cut Line= 2
     1699467.311      491757.615     1699205.116      491999.384
#Sta/Elev= 28
       0  679.66    28.9  678.23    48.2  677.49    57.8  677.16    86.8   676.4
     106   675.7   125.3   674.9   154.2   673.4   163.9  673.46   183.1  673.74
   192.8  673.72   202.4  673.64   212.1  673.44   219.5  673.14   221.7  673.05
   231.3  673.37   234.5  673.99     241  675.25   260.3  684.01   269.9  688.18
   289.2  695.92   298.8  700.22   308.4  705.11   318.1  710.31   327.7   715.6
   337.4  720.83     347  725.95   356.6  730.86
#Mann= 3 , 0 , 0
       0     .06       0   219.5    .045       0   234.5      .1       0
Bank Sta=219.5,234.5
XS Rating Curve= 0 ,0
Exp/Cntr=0.3,0.1

Type RM Length L Ch R = 1 ,5485.1  ,49.7,50.4,51.3
XS GIS Cut Line= 2
     1699526.334      491727.219     1699076.706      491876.997
#Sta/Elev= 30
       0  683.56    38.7  681.23    48.4  680.75      87   678.9   125.7  677.34
   145.1  676.14   193.4  672.54   203.1  672.05     211  671.88   212.8  671.84
   222.4  672.05     226   672.3   232.1  672.72   251.5  674.67   261.1  675.14
   270.8  675.12   290.2  674.67   299.8   674.8   309.5  675.18   319.2  675.92
   328.8  677.12   338.5  678.69   348.2  680.41   367.5  684.16   396.5  690.68
   406.2  692.98   415.9  695.48   425.6  698.34   435.2  701.91   473.9  718.21
#Mann= 3 , 0 , 0
       0     .06       0     211    .045       0     226     .06       0
Bank Sta=211,226
XS Rating Curve= 0 ,0
Exp/Cntr=0.3,0.1

Type RM Length L Ch R = 1 ,5434.7  ,140.9,130.7,120.3
XS GIS Cut Line= 2
     1699501.799      491686.012     1699044.265      491838.424
#Sta/Elev= 30
       0  684.24      59  680.75   108.3  678.17   157.5  674.06   167.3  673.04
   177.2   672.2   183.5  672.01     187   671.9   196.8  672.28   198.5  672.44
   216.5  674.26   226.4  674.87   236.2  675.11     246  675.09   295.3  674.22
   314.9   674.4   324.8  674.71   334.6  675.45   344.5  676.69   354.3  678.27
   364.2  679.67     374  680.77   383.8  682.12   393.7  684.07   403.5  686.52
   423.2  691.94   442.9  696.84   452.7  699.45   462.6   702.5   482.2  709.43
#Mann= 3 , 0 , 0
       0     .06       0   183.5    .045       0   198.5     .06       0
Bank Sta=183.5,198.5
XS Rating Curve= 0 ,0
Exp/Cntr=0.3,0.1

Type RM Length L Ch R = 1 ,5303.9  ,210.3,210.5,210.8
XS GIS Cut Line= 2
     1699341.052      491546.557      1699074.49      491821.352
#Sta/Elev= 27
       0  691.13     9.8  688.86    19.6  686.73    29.4  684.73    39.3  682.78
    49.1  681.17    58.9  679.92    78.5  678.24    88.4  677.32    98.2  676.28
     108  675.18   127.6  672.41   137.4  671.63   138.4  671.63   147.2  671.62
   153.4  671.77   166.9  672.09   225.8  672.96   274.9  673.88   284.7  674.68
   294.5  676.28   314.1  680.12   323.9  682.13   333.8  684.33   343.6  686.82
   363.2  692.03   382.8  696.89
#Mann= 3 , 0 , 0
       0     .06       0   138.4    .045       0   153.4     .06       0
Bank Sta=138.4,153.4
XS Rating Curve= 0 ,0
Exp/Cntr=0.3,0.1

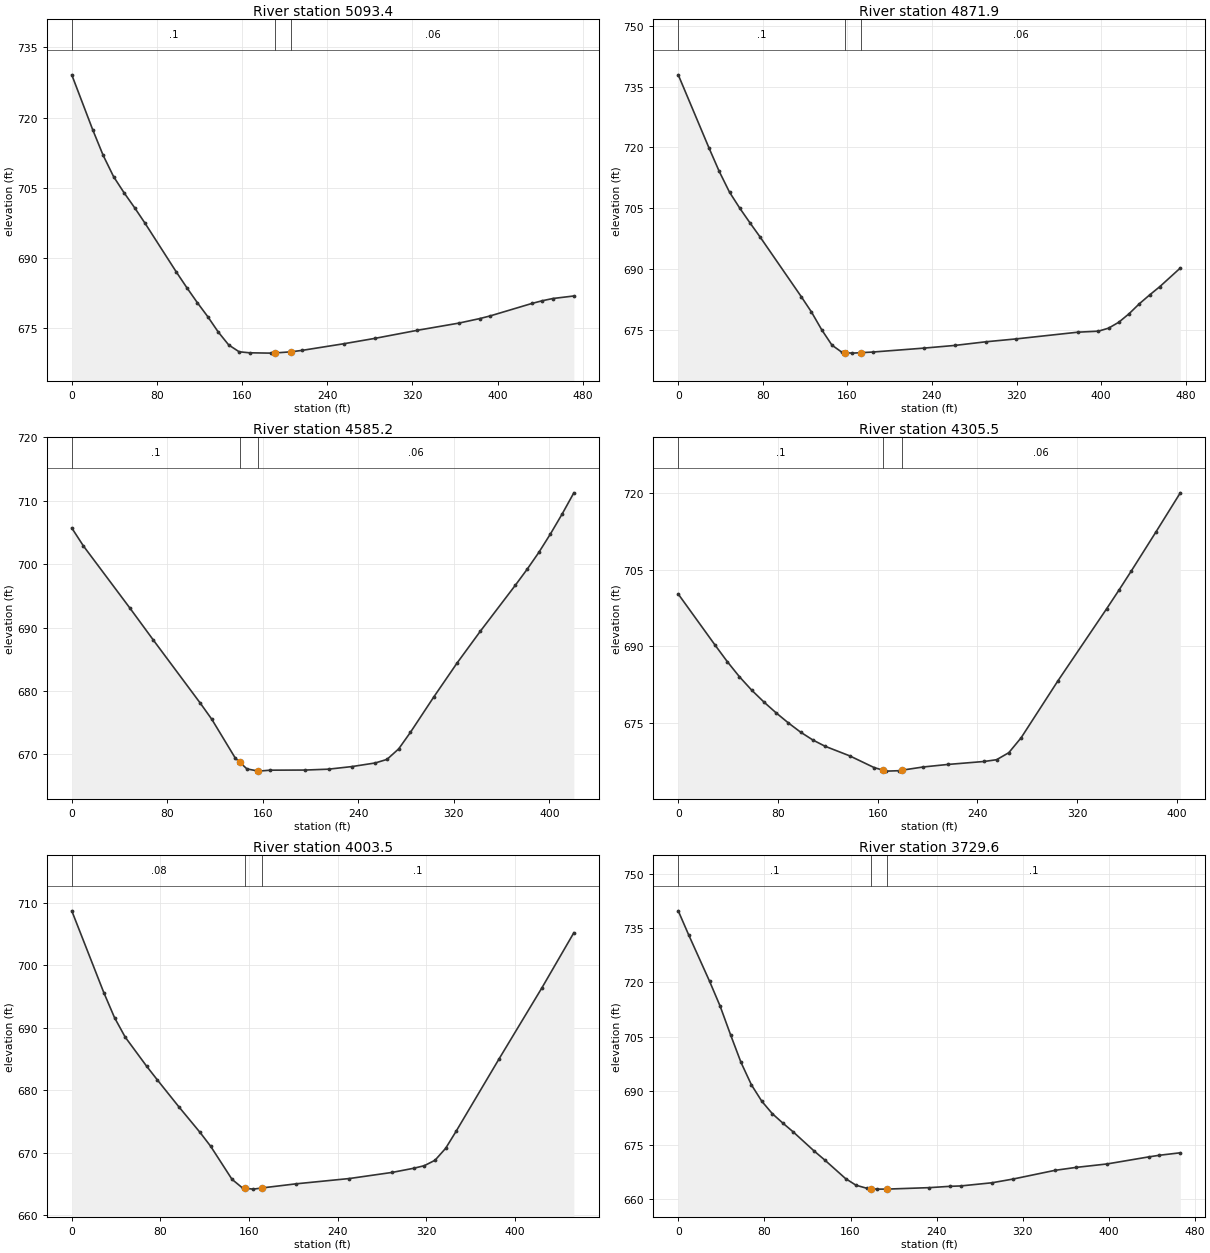
Type RM Length L Ch R = 1 ,5093.4  ,220.6,221.5,222.6
XS GIS Cut Line= 2
     1699204.096      491394.445     1698875.748      491732.934
#Sta/Elev= 29
       0  729.16    19.6  717.47    29.5  711.95    39.3   707.4    49.1  703.97
      59  700.78    68.8  697.46    98.2  687.04   108.1  683.68   117.9   680.5
   127.7  677.51   137.5  674.24   147.4  671.45   157.2  669.99     167  669.77
   186.7   669.7   190.8  669.73   205.8  669.98   216.1  670.28   255.4   671.7
   284.9  672.86   324.2  674.56   363.5  676.11   383.2  677.08     393  677.65
   432.3  680.32   442.1   680.9   451.9  681.37   471.6  681.91
#Mann= 3 , 0 , 0
       0      .1       0   190.8    .045       0   205.8     .06       0
Bank Sta=190.8,205.8
XS Rating Curve= 0 ,0
Exp/Cntr=0.3,0.1

Type RM Length L Ch R = 1 ,4871.9  ,283.5,286.7,289.1
XS GIS Cut Line= 2
     1699039.764       491258.68     1698695.331      491585.611
#Sta/Elev= 29
       0   737.9    29.1  719.88    38.8  714.09    48.5  708.99    58.2  705.05
    67.8  701.45    77.5  697.92   116.3  683.27     126  679.47   135.7  675.09
   145.4   671.3   155.1  669.49   157.9  669.44   164.8  669.33   172.9  669.44
   184.1   669.6   232.6  670.57   261.7  671.23   290.8  672.12   319.8  672.84
     378  674.49   397.4  674.74     407  675.48   416.7  676.94   426.4  679.03
   436.1  681.48   445.8  683.65   455.5  685.71   474.9   690.3
#Mann= 3 , 0 , 0
       0      .1       0   157.9    .045       0   172.9     .06       0
Bank Sta=157.9,172.9
XS Rating Curve= 0 ,0
Exp/Cntr=0.3,0.1

Type RM Length L Ch R = 1 ,4585.2  ,274.2,279.7,284.7
XS GIS Cut Line= 2
     1698864.036       491060.91     1698525.524       491310.34
#Sta/Elev= 28
       0  705.72     9.8  702.87    48.9  693.03    68.4  688.02   107.6   678.1
   117.3  675.54   136.9  669.44   140.9  668.74   146.7  667.72   155.9  667.39
   156.5  667.37   166.2  667.52   195.6  667.54   215.1  667.68   234.7  668.09
   254.2  668.66     264  669.22   273.8  670.88   283.6  673.48   303.1  679.04
   322.7  684.42   342.2  689.44   371.6  696.71   381.4  699.21   391.2  701.87
   400.9  704.78   410.7  707.92   420.5  711.26
#Mann= 3 , 0 , 0
       0      .1       0   140.9    .045       0   155.9     .06       0
Bank Sta=140.9,155.9
XS Rating Curve= 0 ,0
Exp/Cntr=0.3,0.1

Type RM Length L Ch R = 1 ,4305.5  ,300.6,302,302.6
XS GIS Cut Line= 2
     1698729.098      490866.506     1698364.374       491037.38
#Sta/Elev= 29
       0  700.25    29.5  690.29    39.3  687.06    49.1  684.09    58.9  681.48
    68.8  679.14    78.6  677.02    88.4  675.06    98.2  673.26   108.1  671.72
   117.9   670.5   137.5  668.64   157.2  666.34   164.4  665.83     167  665.65
   176.8  665.73   179.4  665.83   196.5  666.46   216.1  666.95   245.6  667.54
   255.4  667.88   265.2  669.25   275.1  672.17   304.5  683.25   343.8  697.41
   353.6  701.02   363.5  704.76   383.1  712.32   402.8  720.02
#Mann= 3 , 0 , 0
       0      .1       0   164.4    .045       0   179.4     .06       0
Bank Sta=164.4,179.4
XS Rating Curve= 0 ,0
Exp/Cntr=0.3,0.1

Type RM Length L Ch R = 1 ,4003.5  ,265.9,273.9,286.6
XS GIS Cut Line= 2
     1698646.371      490604.348     1698226.817      490776.115
#Sta/Elev= 25
       0  708.71    28.9  695.63    38.6  691.61    48.2   688.5    67.5  683.85
    77.2  681.65    96.5  677.37   115.8  673.23   125.4  671.01   144.7  665.71
   154.3  664.31   156.8  664.27     164  664.14   171.8  664.33   202.6  664.99
   250.8  665.84   289.4  666.82   308.7  667.48   318.3  667.89     328  668.76
   337.6  670.67   347.2  673.44   385.8  684.98   424.4  696.33   453.4   705.2
#Mann= 3 , 0 , 0
       0     .08       0   156.8    .045       0   171.8      .1       0
Bank Sta=156.8,171.8
XS Rating Curve= 0 ,0
Exp/Cntr=0.3,0.1

Type RM Length L Ch R = 1 ,3729.6  ,88.5,82.2,70.6
XS GIS Cut Line= 2
      1698591.02      490365.457     1698147.073      490508.036
#Sta/Elev= 30
       0  739.83     9.7  733.17    29.1  720.33    38.9  713.46    48.6  705.52
    58.3  697.87      68  691.65    77.7  687.09    87.4  683.68    97.1  681.09
   106.9  678.61   126.3  673.33     136  670.88   155.4  665.72   165.1  663.88
   174.9  663.06   179.1  662.95   184.6   662.8   194.1  662.81   233.1  663.21
   252.6  663.58   262.3  663.68   291.4  664.56   310.8  665.58   349.7  667.99
   369.1   668.8   398.3  669.77   437.1  671.73   446.8  672.17   466.3  672.86
#Mann= 3 , 0 , 0
       0      .1       0   179.1    .045       0   194.1      .1       0
Bank Sta=179.1,194.1
XS Rating Curve= 0 ,0
Exp/Cntr=0.3,0.1

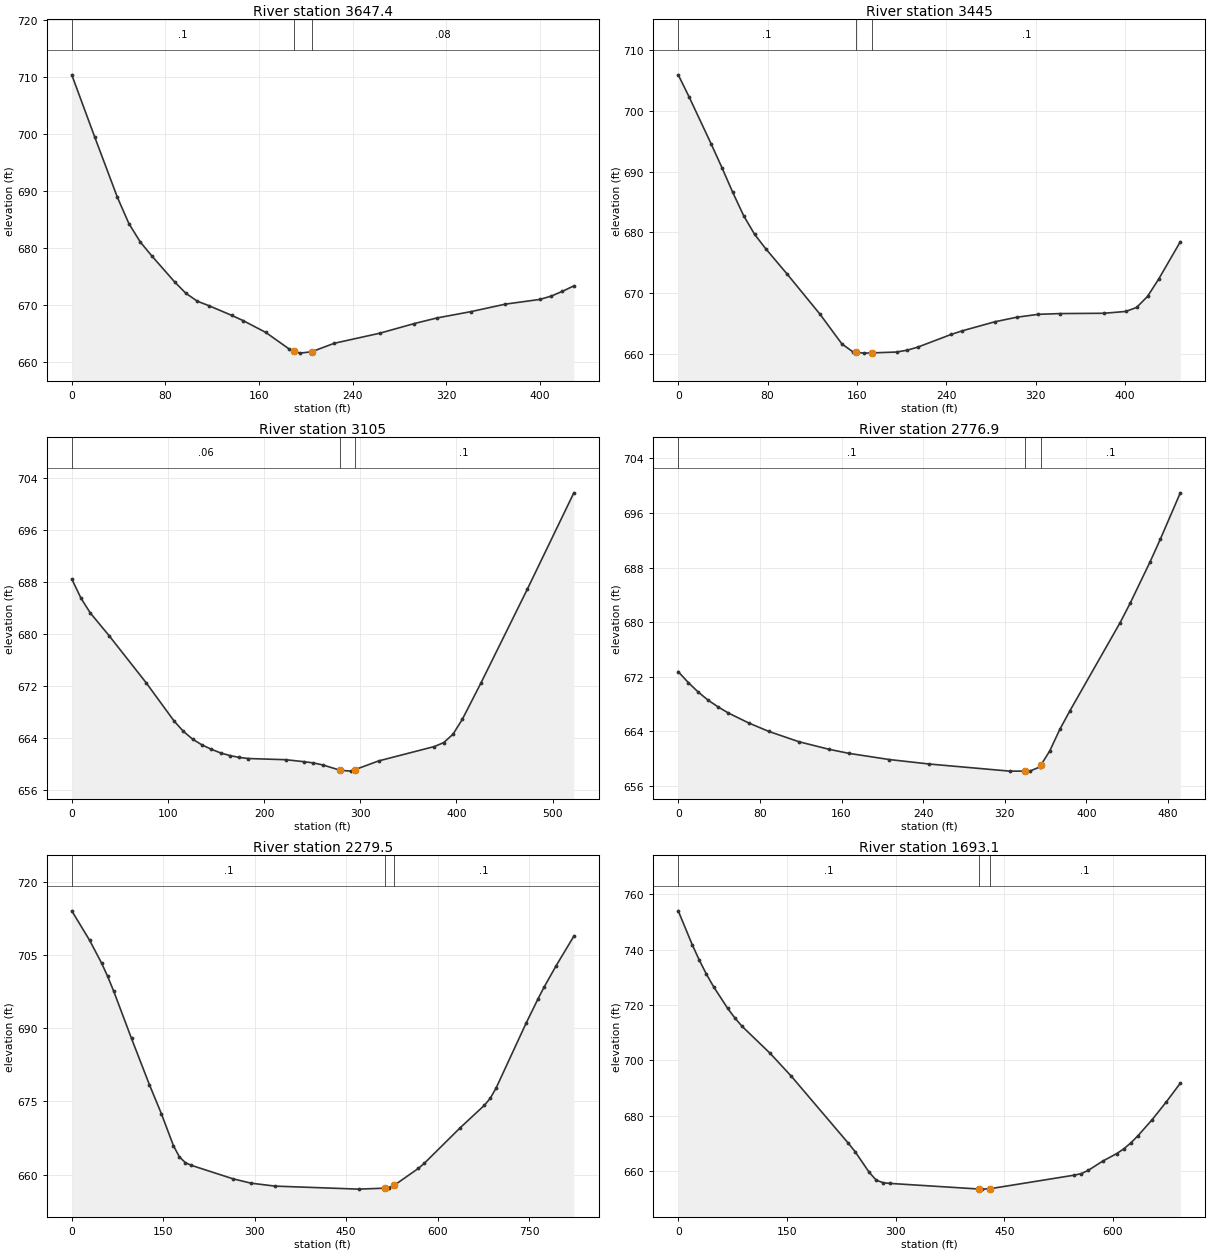
Type RM Length L Ch R = 1 ,3647.4  ,199.6,202.4,204.7
XS GIS Cut Line= 2
     1698543.937      490311.644     1698135.434       490442.84
#Sta/Elev= 27
       0   710.4    19.5  699.55      39   688.9    48.8  684.31    58.5  681.08
    68.3  678.65    87.8  674.09    97.5  672.07   107.3  670.68     117  669.91
   136.5  668.21   146.3  667.29   165.8   665.2   185.3  662.36     190  661.98
     195  661.57     205  661.81   224.3   663.3   263.3  665.07   292.5  666.75
     312  667.74   341.3  668.86   370.6  670.17   399.8  670.99   409.6  671.57
   419.3  672.42     429  673.37
#Mann= 3 , 0 , 0
       0      .1       0     190    .045       0     205     .08       0
Bank Sta=190,205
XS Rating Curve= 0 ,0
Exp/Cntr=0.3,0.1

Type RM Length L Ch R = 1 ,3445    ,345.3,340,333
XS GIS Cut Line= 2
     1698537.204      490156.683     1698099.193       490257.21
#Sta/Elev= 30
       0  705.87     9.8  702.22    29.3   694.6    39.1  690.65    48.8  686.58
    58.6  682.74    68.4  679.68    78.2  677.36    97.7  673.13     127  666.56
   146.5  661.71   156.3  660.42   158.8  660.36   166.1   660.2   173.8  660.24
   195.4  660.38   205.2  660.69   214.9  661.22   244.2  663.26     254  663.85
   283.3  665.34   302.9  666.09   322.4  666.57   341.9  666.69     381  666.74
   400.6  667.04   410.3   667.7   420.1  669.52   429.9  672.31   449.4  678.48
#Mann= 3 , 0 , 0
       0      .1       0   158.8    .045       0   173.8      .1       0
Bank Sta=158.8,173.8
XS Rating Curve= 0 ,0
Exp/Cntr=0.3,0.1

Type RM Length L Ch R = 1 ,3105    ,330.5,328.1,325.1
XS GIS Cut Line= 2
     1698431.478      489824.987     1697952.387      490032.834
#Sta/Elev= 29
       0   688.5     9.7  685.52    19.3  683.27    38.7   679.8    77.4  672.52
   106.4  666.64     116  665.06   125.7  663.84   135.4  662.96   145.1  662.29
   154.7  661.73   164.4  661.32   174.1  661.03   183.8  660.86   222.4  660.68
   241.8  660.37   251.4  660.18   261.1  659.87   279.1  659.06   290.1  658.92
   294.1  659.12   319.1  660.49   377.2  662.71   386.8  663.31   396.5   664.6
   406.2   666.9   425.5  672.47   473.9  686.96   522.2  701.77
#Mann= 3 , 0 , 0
       0     .06       0   279.1    .045       0   294.1      .1       0
Bank Sta=279.1,294.1
XS Rating Curve= 0 ,0
Exp/Cntr=0.3,0.1

Type RM Length L Ch R = 1 ,2776.9  ,487.5,497.4,498.8
XS GIS Cut Line= 2
     1698251.714      489515.877     1697829.117      489767.839
#Sta/Elev= 26
       0  672.76     9.8  671.17    19.7  669.76    29.5  668.56    39.4  667.57
    49.2   666.7    68.9  665.26    88.6  664.02   118.1  662.51   147.6   661.4
   167.3   660.8   206.6   659.9     246  659.24   324.7   658.2   340.2   658.2
   344.4   658.2   354.2   658.8   355.2  659.04   364.1  661.17   373.9  664.31
   383.8  667.03     433  679.93   442.8  682.76   462.5  688.87   472.3  692.11
     492  698.93
#Mann= 3 , 0 , 0
       0      .1       0   340.2    .045       0   355.2      .1       0
Bank Sta=340.2,355.2
XS Rating Curve= 0 ,0
Exp/Cntr=0.3,0.1

Type RM Length L Ch R = 1 ,2279.5  ,630.3,586.4,619.7
XS GIS Cut Line= 2
     1698211.596      489122.751     1697421.912      489356.776
#Sta/Elev= 30
       0  714.16    29.4  708.08      49   703.4    58.8  700.71    68.6  697.72
      98  687.94   127.5  678.41   147.1  672.46   166.7  665.95   176.5  663.63
   186.3  662.44   196.1  661.89   264.7  659.11   294.2  658.22   333.4  657.62
   470.6     657   514.1   657.2   519.7   657.3   529.1   657.8   568.7  661.27
   578.5  662.33   637.3  669.62   676.6  674.19   686.4  675.64   696.2   677.8
   745.2  691.06   764.8  696.07   774.6  698.45   794.2  702.81   823.6  708.96
#Mann= 3 , 0 , 0
       0      .1       0   514.1    .045       0   529.1      .1       0
Bank Sta=514.1,529.1
XS Rating Curve= 0 ,0
Exp/Cntr=0.3,0.1

Type RM Length L Ch R = 1 ,1693.1  ,337.2,335,329.3
XS GIS Cut Line= 2
     1698139.322      488711.731     1697466.393      488877.376
#Sta/Elev= 30
       0  754.01    19.5  741.65    29.3  736.07      39  731.07    48.8  726.59
    68.3  718.73    78.1  715.31    87.8  712.35   126.9  702.49   156.2   694.2
   234.3  670.16     244  667.02   263.5  659.52   273.3  656.66   283.1  655.72
   292.8  655.48   415.4  653.45   419.7  653.42   430.4  653.57   546.6  658.47
   556.4  659.03   566.1  660.23   585.6   663.5   605.2  666.27   614.9  667.96
   624.7  670.13   634.4  672.68     654  678.49   673.5  684.89     693  691.72
#Mann= 3 , 0 , 0
       0      .1       0   415.4    .045       0   430.4      .1       0
Bank Sta=415.4,430.4
XS Rating Curve= 0 ,0
Exp/Cntr=0.3,0.1

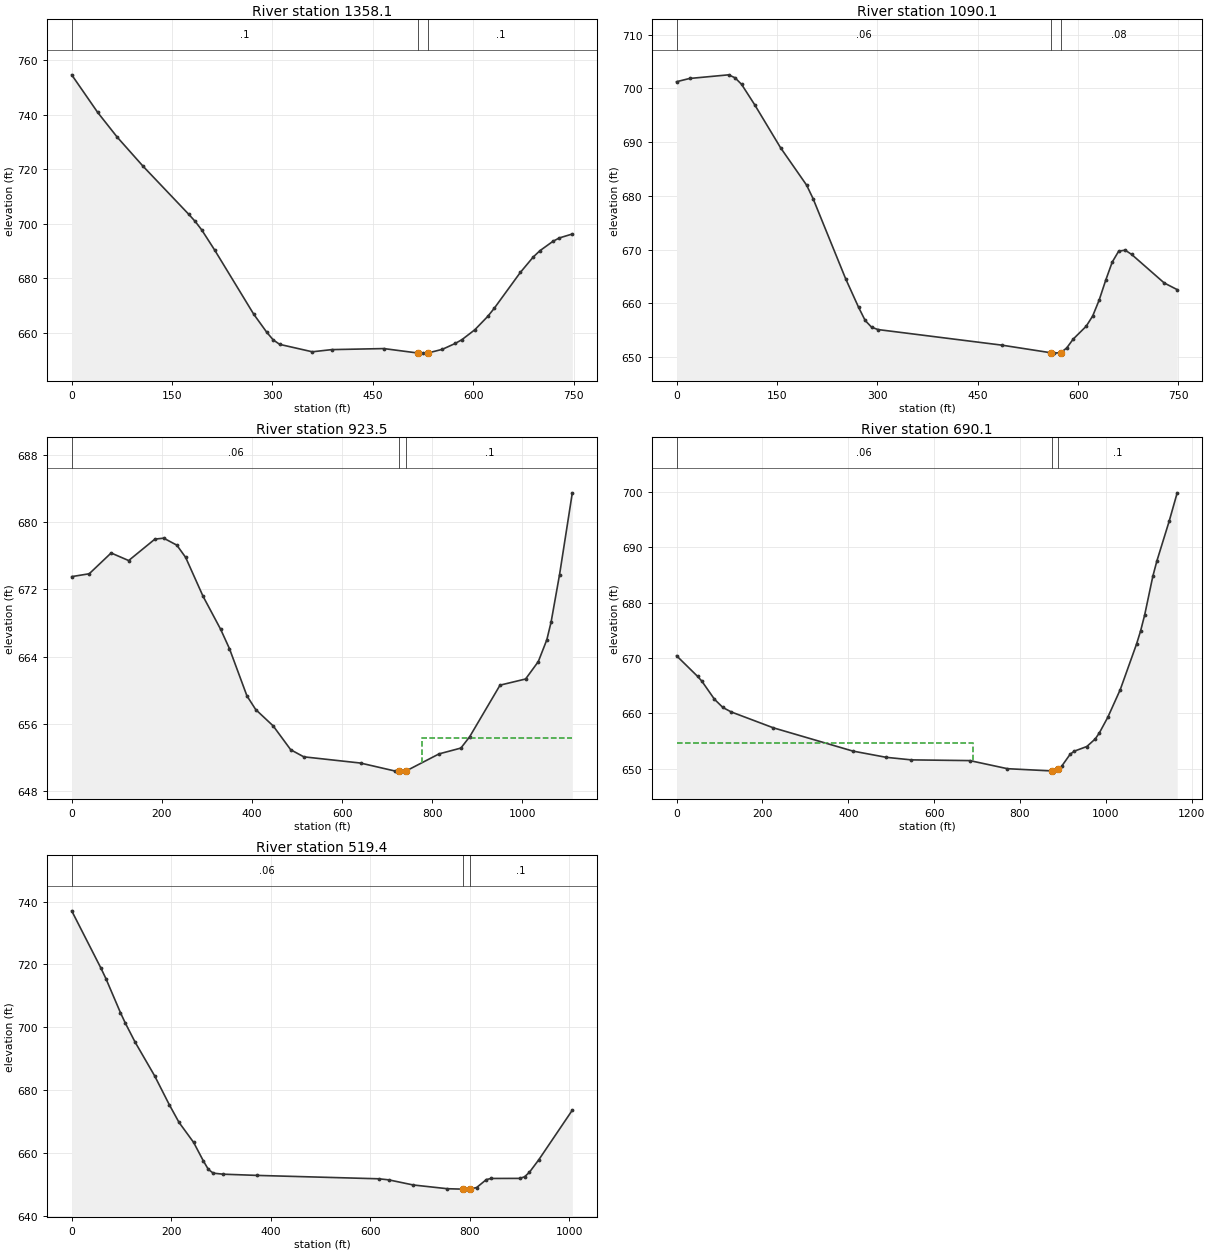
Type RM Length L Ch R = 1 ,1358.1  ,268.1,268,267.2
XS GIS Cut Line= 2
     1698060.657      488365.089     1697376.169      488667.028
#Sta/Elev= 30
       0  754.71    38.9   740.9      68  731.85   106.9   721.1   174.9  703.54
   184.6   700.9   194.3  697.81   213.8  690.35     272  666.88   291.5  660.24
   301.2  657.43   310.9   655.8   359.5  653.08   388.6  653.88   466.4  654.26
   517.8  652.61   524.7  652.59   532.8  652.67   553.8  653.98   573.2  656.15
     583  657.51   602.4  661.16   621.8  666.09   631.5  669.07   670.4   682.2
   689.8  687.89   699.6  690.16     719  693.59   728.7  694.86   748.1   696.3
#Mann= 3 , 0 , 0
       0      .1       0   517.8    .045       0   532.8      .1       0
Bank Sta=517.8,532.8
XS Rating Curve= 0 ,0
Exp/Cntr=0.3,0.1

Type RM Length L Ch R = 1 ,1090.1  ,179.9,166.6,151
XS GIS Cut Line= 2
     1697974.706      488133.258     1697290.218      488435.198
#Sta/Elev= 30
       0  701.23    19.4  701.83    77.7  702.51    87.4  701.96    97.2  700.73
   116.6  696.97   155.4  688.95   194.3     682     204  679.48   252.6   664.6
     272  659.27   281.8  656.83   291.5  655.56   301.2  655.13   485.8  652.24
   559.2  650.82   563.5  650.75   574.2  650.85     583  651.71   592.7  653.36
   612.1  655.75   621.8  657.65   631.5  660.62   641.2  664.28     651  667.68
   660.7  669.72   670.4   669.9   680.1   669.1   728.7   663.8   748.1  662.56
#Mann= 3 , 0 , 0
       0     .06       0   559.2    .045       0   574.2     .08       0
Bank Sta=559.2,574.2
XS Rating Curve= 0 ,0
Exp/Cntr=0.3,0.1

Type RM Length L Ch R = 1 ,923.5   ,166.9,233.4,238.2
XS GIS Cut Line= 4
     1697906.384        487634.1     1697609.519      487981.444
     1697316.319      488366.764     1697226.322      488510.775
#Sta/Elev= 30
       0  673.52    38.9  673.86    87.5  676.33   126.4  675.43   184.7  677.98
   204.2  678.09   233.3  677.26   252.8  675.81   291.6  671.17   330.5  667.26
     350  664.97   388.9  659.34   408.3  657.72   447.2  655.77     486  652.94
     515   652.1   640.9  651.36   718.4   650.4   727.3   650.4   742.3  650.43
   815.2  652.45   863.6  653.14     883  654.48   950.5  660.62  1007.2  661.35
  1035.4  663.42  1054.3  666.01  1063.8  668.12  1082.6  673.77  1110.9  683.48
#Mann= 3 , 0 , 0
       0     .06       0   727.3    .045       0   742.3      .1       0
#XS Ineff= 2 , 0
                          777.46           654.3
Permanent Ineff=
       F       F
Bank Sta=727.3,742.3
XS Rating Curve= 0 ,0
Exp/Cntr=0.3,0.1

Type RM Length L Ch R = 1 ,690.1   ,262.1,170.7,153
XS GIS Cut Line= 4
      1697817.22      487599.217      1697662.58      487749.689
     1697166.413      488399.788     1697109.765      488519.737
#Sta/Elev= 30
       0   670.4      49  666.68    58.8  665.83    88.3  662.55   107.9  661.07
   127.5  660.26   225.5   657.4   410.5  653.21   488.4  652.08   546.8  651.62
   683.1  651.49   770.7  650.03   874.6  649.62   877.8  649.59   889.6  649.93
   897.3   650.5   916.8  652.63   926.5  653.19   955.7  654.03   975.2  655.39
   984.9  656.49  1004.4  659.28  1033.6   664.3  1071.5  672.51    1081  674.89
  1090.4  677.75  1109.4  684.72  1118.8  687.48  1147.3  694.62  1166.2  699.79
#Mann= 3 , 0 , 0
       0     .06       0   874.6    .045       0   889.6      .1       0
#XS Ineff= 2 , 0
          689.58  654.59
Permanent Ineff=
       F       F
Bank Sta=874.6,889.6
XS Rating Curve= 0 ,0
Exp/Cntr=0.3,0.1

Type RM Length L Ch R = 1 ,519.4   ,447.8,519.4,527.8
XS GIS Cut Line= 3
     1697404.444      487495.352     1697093.621      488269.067
     1697125.121      488438.945
#Sta/Elev= 30
       0  737.05    58.9  718.81    68.7  715.55    98.1  704.68   107.9  701.36
   127.5  695.34   166.8  684.62   196.2  675.47   215.8  669.84   245.2  663.47
   264.9  657.55   274.7  654.93   284.5  653.72   304.1  653.39   372.8     653
     618  651.92   637.6  651.58   686.7  649.96   755.3  648.77   784.8  648.64
   786.1  648.64   801.1  648.67   814.2  649.15   833.8  651.68   843.4  652.03
     901  652.05   910.6  652.57   920.2  653.97   939.4  658.02  1006.6  673.73
#Mann= 3 , 0 , 0
       0     .06       0   786.1    .045       0   801.1      .1       0
Bank Sta=786.1,801.1
XS Rating Curve= 0 ,0
Exp/Cntr=0.3,0.1

Chan Stop Cuts=-1
Use User Specified Reach Order=0
Composite Channel Slope=5